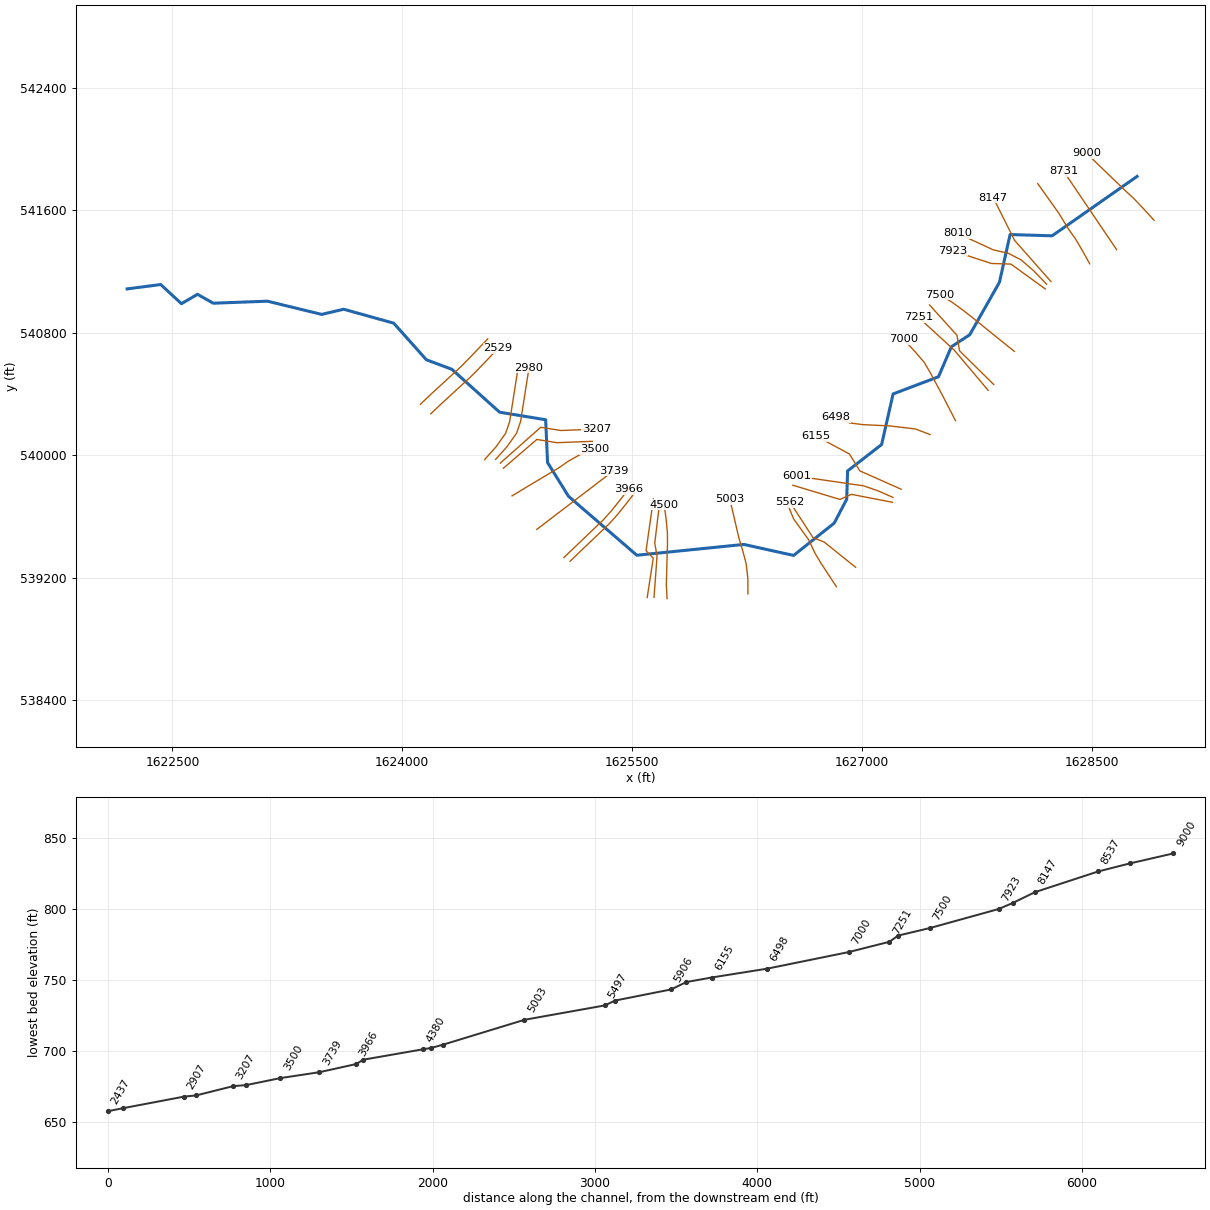
--- JimRn.prj (project) ---

Proj Title=JimRn
Current Plan=p01
Default Exp/Contr=0,0
English Units
Geom File=g01
Flow File=f01
Plan File=p01
Background Map Layer=Inundation Boundary (P100yr Value_0)
BEGIN DESCRIPTION:
Stream Name: Jim Run
Flood Zone: AFH
Marshall County, WV
HEC-RAS Version: RAS 6.6
Vertical Datum: NAVD88
Projection: NAD 1983 StatePlane West Virginia N FIPS 4701 (US Feet)
Terrain: 1-meter West Virginia FEMA R3 South Central (collected 2018-2019)
Land Use: 2024 NLCD
Hydrologic Method:
Duda et al., "Estimation of magnitude and frequency of floods for rural, unregulated streams in and near Virginia and West Virginia." September 8, 2025.
Additional Model Notes:
None
END DESCRIPTION:
DSS Export Rating Curves= 0
DSS Export Rating Curve Sorted= 0
DSS Export Volume Flow Curves= 0
DXF OffsetX= 0
DXF OffsetY= 0
DXF ScaleX= 0
DXF ScaleY= 0

--- JimRn.p01 (plan) ---

Plan Title=Floodplain
Program Version=6.60
Short Identifier=Floodplain
Geom File=g01
Flow File=f01
Subcritical Flow
K Sum by GR= 0
Std Step Tol= 0.01
Critical Tol= 0.01
Num of Std Step Trials= 20
Max Error Tol= 0.3
Flow Tol Ratio= 0.001
Split Flow NTrial= 30
Split Flow Tol= 0.02
Split Flow Ratio= 0.02
Log Output Level= 0
Friction Slope Method= 1
Unsteady Friction Slope Method= 2
Unsteady Bridges Friction Slope Method= 1
Parabolic Critical Depth
Global Vel Dist= 0 , 0 , 0
Global Log Level= 0
CheckData=False
Encroach Param=-1 ,0,0, 0
Flow Ratio Tolerance=0.1
Flow Ratio Min Ratio=0.5
Flow Ratio Max Ratio=4
Flow Ratio Max Iterations= 10
Mapping Interval=1HOUR
Computation Time Step Use Courant=        0
Computation Time Step Use Time Series=    0
Computation Time Step Count To Double=0
Computation Time Step Max Doubling=0
Computation Time Step Max Halving=0
Computation Time Step Residence Courant=0
Run HTab= 0
Run UNet= 0
Run Sediment= 0
Run PostProcess= 0
Run WQNet= 0
Run RASMapper=-1
UNET Theta= 0
UNET Theta Warmup= 0
UNET ZTol= 0
UNET ZSATol= 0
UNET MxIter= 0
UNET Max Iter WO Improvement= 0
UNET MaxInSteps= 0
UNET DtIC= 0
UNET DtMin= 0
UNET MaxCRTS= 0
UNET WFStab= 0
UNET SFStab= 0
UNET WFX= 1
UNET SFX= 1
UNET Gravity=32.17405
UNET 1D Methodology=Finite Difference
UNET DSS MLevel= 1
UNET Pardiso=0
UNET DZMax Abort= 0
UNET Use Existing IB Tables= 0
UNET Froude Reduction=False
UNET Froude Limit= 0
UNET Froude Power= 0
UNET D1 Cores= 0
UNET WindReference=Eulerian
UNET WindDragFormulation=Hsu (1988)
UNET D2 Coriolis=0
UNET D2 Cores= 0
UNET D2 Theta= 1
UNET D2 Theta Warmup= 1
UNET D2 Z Tol= 0.01
UNET D2 Volume Tol= 0.01
UNET D2 Max Iterations= 20
UNET D2 Advanced Convergence=0
UNET D2 WS Max Tol=0.15
UNET D2 WS RMS Tol=0.002
UNET D2 WS Stall Tol=1
UNET D2 Equation= 0
UNET D2 RampUpFraction=0.1
UNET D2 TimeSlices= 1
UNET D2 Turbulence Formulation=Non-Conservative (original)
UNET D2 Eddy Viscosity=0.3
UNET D2 Transverse Eddy Viscosity=0.1
UNET D2 Smagorinsky Mixing=0
UNET D2 BCVolumeCheck=0
UNET D2 Cores=0
UNET D2 SolverType=PARDISO (Direct)
UNET D2 Minimum Iterations= 3
UNET D2 Maximum Iterations= 30
UNET D2 Restart Number= 10
UNET D2 Relaxation Coeff=1.3
UNET D2 SOR Precondition Iterations= 10
UNET D2 ILUT Maximum Fill= 8
UNET D2 ILUT Tolerance=1E-08
UNET D2 Convergence Tolerance=0.00001
PS Theta= 1
PS WS Tol= 0.01
PS Volume Tol= 0.01
PS Max Iterations= 20
PS Equation= 0
PS Advance Time Step=-1
PS Target Courant=0.9
PS Time Slices= 1
PS Iterate With 2D=0
PS Project Initial WSE from DS=-1
PS Ramp Up Initial WSE from US=-1
PS Cores=0
UNET D1D2 MaxIter= 0
UNET D1D2 ZTol=0.01
UNET D1D2 QTol=0.1
UNET D1D2 MinQTol=1
Write IC File= 0
Write IC File at Fixed DateTime=0
Write IC File at Sim End=0
Echo Input=False
Echo Parameters=False
Echo Output=False
Write Detailed= 0
HDF Write Warmup=0
HDF Write Time Slices=0
HDF Flush=0
HDF Compression= 1
HDF Chunk Size= 1
HDF Spatial Parts= 1
HDF Use Max Rows=0
HDF Fixed Rows= 1
Calibration Method= 0
Calibration Iterations= 20
Calibration Max Change=0.05
Calibration Tolerance=0.2
Calibration Maximum=1.5
Calibration Minimum=0.5
Calibration Optimization Method= 1
WQ AD Non Conservative
WQ ULTIMATE=-1
WQ Max Comp Step=1HOUR
WQ Output Interval=15MIN
WQ Output Selected Increments= 0
WQ Create Restart=0
WQ Fixed Restart=0
WQ System Summary=0
WQ Write To DSS=0
Sorting and Armoring Iterations= 10
XS Update Threshold= 0.02
Bed Roughness Predictor= 0
Processes Affected by Predictor=Sediment Only
Hydraulics Update Threshold= 0.02
Energy Slope Method= 1
Volume Change Method= 1
Sediment Retention Method= 0
Sediment TS Multiplier= 1
Warm Up Method= 0
XS Weighting Method= 0
Number of US Weighted Cross Sections= 1
Number of DS Weighted Cross Sections= 1
Upstream XS Weight=0
Main XS Weight=1
Downstream XS Weight=0
Number of DS XS's Weighted with US Boundary= 1
Upstream Boundary Weight= 1
Weight of XSs Associated with US Boundary= 0
Number of US XS's Weighted with DS Boundary= 1
Downstream Boundary Weight= 0.5
Weight of XSs Associated with DS Boundary= 0.5
Percentile Method= 0
Sediment Output Level= 3
Mass or Volume Output= 0
Output Increment Type= 1
Profile and TS Output Increment= 1
Transport Output Increment 1
XS Output Flag= 0
XS Output Increment= 10
Read HDF5 Sediment Hotstart= 0
Sediment Hotstart Type= 0
Write Gradation File= 0
Read Gradation Hotstart= 0
Write HDF5 File= 1
Write Binary Output= 1
Write DSS Sediment File= 0
DSS Sediment Output Type= 1
SV Curve= 0
Specific Gage Flag= 0
Subcell Erosion Methods= 0
Subcell Deposition Methods= 0
Advection Scheme= 1
Matrix Solver= 0
Implicit Weighting Factor= 1
Maximum Outer Loop Convergence Iterations= 5
Convergence Maximum Absolute= 0.001
Convergence RMSE= 0.0001
Grain Fractions Max Abs Error= 0.001
Max Subgrid Regions= 1
Max Subgrid Length Scale= 3.402823E+38
Initial Layer Thickness= 3
Min Layer Thickness= 0.1
Max Layer Thickness= 6
Number of Layers= 5

--- JimRn.f01 (steady flow) ---

Flow Title=Flow
Program Version=6.60
Number of Profiles= 1
Profile Names=P100yr
River Rch & RM=JimRn,Main            ,9000
     694
River Rch & RM=JimRn,Main            ,8147
     799
River Rch & RM=JimRn,Main            ,6498
     916
River Rch & RM=JimRn,Main            ,3290
    1050
Boundary for River Rch & Prof#=JimRn,Main            , 1
Up Type= 0
Dn Type= 3
Dn Slope=0.01
DSS Import GetInterval= 0
DSS Import GetPeak= 0
DSS Import FillOption= 0

--- JimRn.g01 (geometry) ---

Geom Title=Geometry
Program Version=6.60

River Reach=JimRn           ,Main
Reach XY= 30
     1628796.889       541820.43     1628242.355      541432.655
     1627967.787      541440.852     1627898.321       541129.21
     1627704.374      540786.652     1627584.711      540708.564
     1627500.266       540512.42     1627204.179       540400.41
     1627129.247       540070.17      1626907.15       539897.74
     1626901.163       539712.69     1626819.736      539557.154
     1626554.763      539346.274     1626230.176      539418.011
     1625531.119      539347.394     1625085.207      539732.254
     1624948.475      539952.776     1624936.131      540231.769
     1624635.444      540281.147     1624323.701      540561.444
      1624157.39      540623.351     1623944.509      540862.221
     1623617.643      540953.384     1623474.352      540919.509
     1623119.969      541005.843     1622766.051      540992.693
     1622663.471      541050.852     1622558.603      540989.487
     1622423.214      541114.608     1622204.081      541086.003

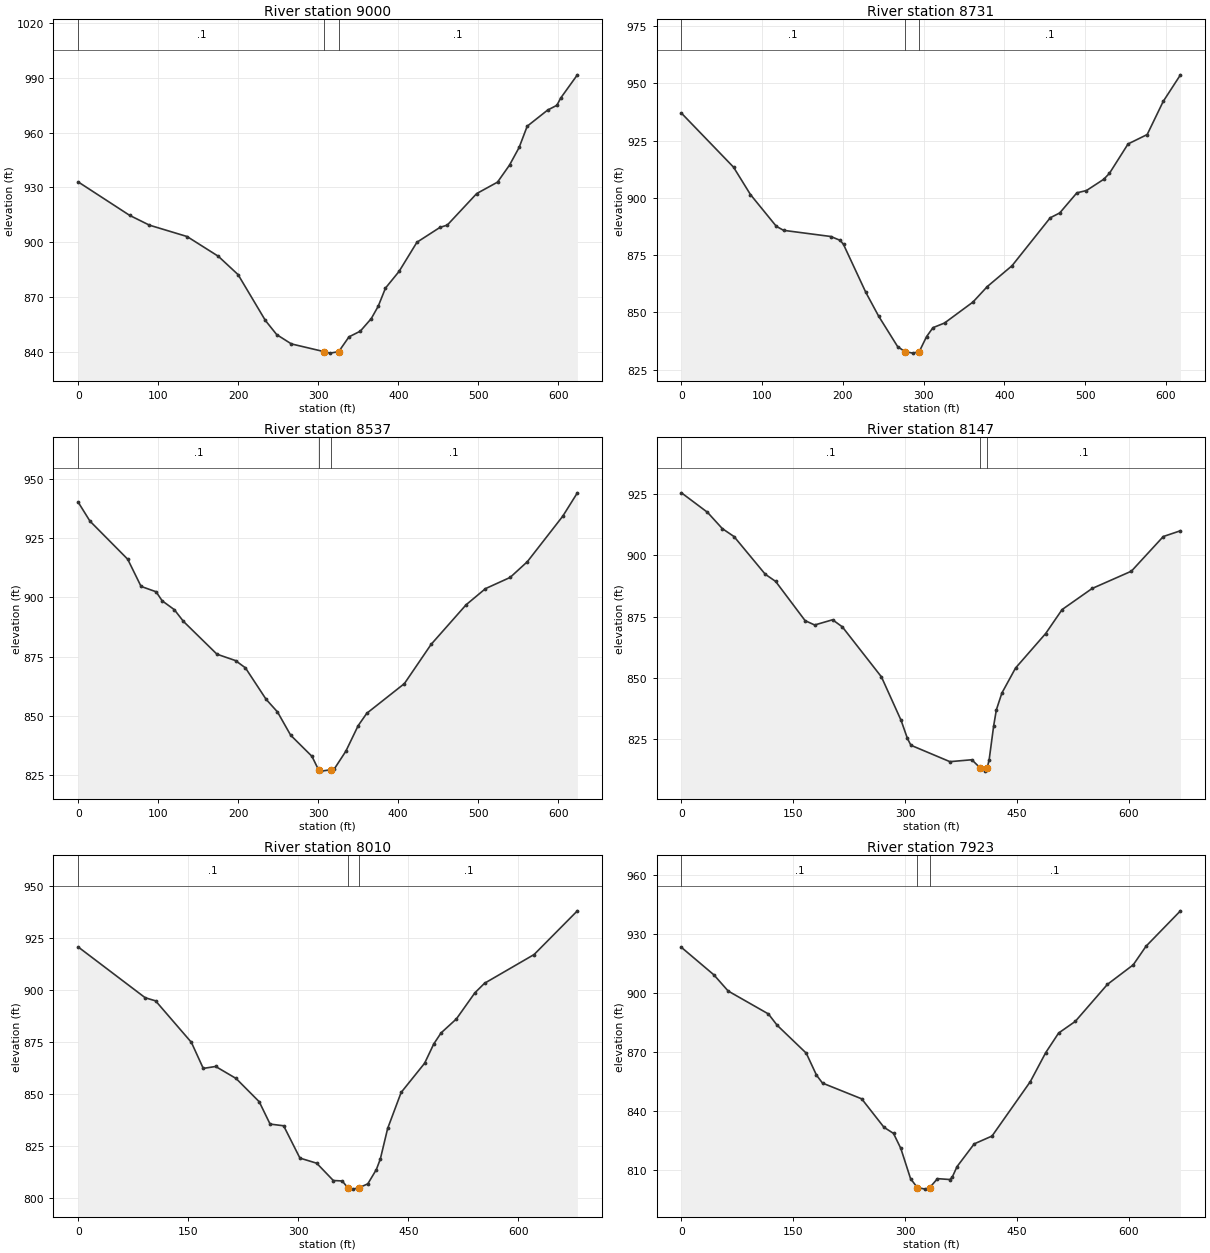
Type RM Length L Ch R = 1 ,9000    ,268.8,269.1,265.9
XS GIS Cut Line= 6
1628907.77059571541533.8302875611628841.17558455541606.817346305
1628777.43063331 541674.149560721628721.74406488 541725.57695131
1628649.82065231541795.0758280611628465.36235981541972.949816138
#Sta/Elev= 30
       0  932.98    64.1  914.74    88.8  909.38   135.8  903.17   174.9  892.36
   199.6  882.31   233.7  857.24   247.9  849.48   266.2   844.4   307.2  840.16
   314.5  839.36   325.3840.1667   338.2  848.27   352.3  851.37     366  858.23
   374.7     865   383.8  874.95   400.8  884.09   423.1  900.03   451.9  908.16
     461  909.41   497.8  926.67   523.8  932.92   538.8  942.25   550.8  951.89
   560.9  963.52   586.4  972.34     598  974.97   602.7   978.9   623.6  991.64
#Mann= 3 ,-1,0
       0      .1       0   307.2    .045       0   325.3      .1       0
Bank Sta=307.2,325.3
XS Rating Curve= 0 ,0
Exp/Cntr(USF)=0,0
Exp/Cntr=0.3,0.1

Type RM Length L Ch R = 1 ,8731    ,196,194.2,194.5
XS GIS Cut Line= 2
1628662.85594098541342.7249192621628316.88864479541854.811433077
#Sta/Elev= 30
       0  936.93    64.5  913.38    85.5  901.41   117.5  887.58   126.5  885.83
     185  883.14   196.7  881.44   200.7  879.66   228.4  858.73   244.2  848.41
   267.7  835.14   276.6832.9508   286.6  832.28   294.5  832.95   303.6   839.5
   311.5  843.38   325.8  845.41     361  854.55   378.8  861.32   409.4  870.39
   456.7   891.3   468.5  893.42   489.7  902.18   501.6  903.19   522.9  908.08
     530  910.67   553.1   923.5   576.8  927.61   596.6  942.04     618  953.65
#Mann= 3 ,-1,0
       0      .1       0   276.6    .045       0   294.5      .1       0
Bank Sta=276.6,294.5
XS Rating Curve= 0 ,0
Exp/Cntr(USF)=0,0
Exp/Cntr=0.3,0.1

Type RM Length L Ch R = 1 ,8537    ,389,389.3,385.3
XS GIS Cut Line= 6
1628487.45979733541250.159613599  1628440.143619541335.343826432
1628393.98557484541414.0070549291628348.92759408541476.968543191
1628284.91467104541581.292666889  1628148.530029541773.269459773
#Sta/Elev= 30
       0  940.09    14.5  932.21    61.7  916.12    78.4  904.64    97.2  902.37
   104.8  898.55     120  894.81   131.4  889.86   173.3  876.01   196.5  873.31
   208.9  870.24   234.7  856.98     249  851.62   265.5  841.78   292.1  832.87
  300.39  827.15   303.7  826.62   315.4  827.19   320.2  827.63   334.5  835.05
   349.9  845.84   360.7  851.06   407.7  863.59   441.1  880.15   484.9  896.89
   509.1   903.7   539.9  908.42   561.4  915.06   605.7  934.28     624  944.16
#Mann= 3 ,-1,0
       0      .1       0  300.39    .045       0   315.4      .1       0
Bank Sta=300.39,315.4
XS Rating Curve= 0 ,0
Exp/Cntr(USF)=0,0
Exp/Cntr=0.3,0.1

Type RM Length L Ch R = 1 ,8147    ,132.1,136.9,142.1
XS GIS Cut Line= 3
1628234.51547902541134.0462326671627997.00618441541403.131907487
1627858.34468872541680.454898882
#Sta/Elev= 30
       0  925.54    34.9  917.59    54.7  910.97    70.5   907.7   112.3  892.35
   126.3   889.4   165.8   873.4   178.6  871.64   202.6  873.76   215.7  870.87
   268.1  850.47   294.5   832.7   302.9  825.38   307.6  822.59   359.9  815.89
   389.3  816.67   400.6813.2938   407.6  812.03   409.8813.3141   412.5  816.62
   418.6  830.57   422.2  837.05   429.6  843.89   447.9  854.08   488.3  868.16
   510.3  877.92   550.6  886.53   603.2  893.58     646  907.72     669  910.07
#Mann= 3 ,-1,0
       0      .1       0   400.6    .045       0   409.8      .1       0
Bank Sta=400.6,409.8
XS Rating Curve= 0 ,0
Exp/Cntr(USF)=0,0
Exp/Cntr=0.3,0.1

Type RM Length L Ch R = 1 ,8010    ,86.2,87.2,89
XS GIS Cut Line= 6
1628205.68702614541117.4023146481628124.76920897541201.515663475
1628040.15487689541275.2500960531627956.87026656541318.205062643
1627857.99448006541341.0642688871627625.32959105541448.446928144
#Sta/Elev= 30
       0  920.81    91.1  896.46   105.3  894.95   154.1  874.99   170.3  862.46
   187.2  863.39     215  857.63   246.6  846.43   261.4  835.68   279.9  834.86
   302.1  819.32     325  816.85   347.6  808.54   359.8  808.32   367.1805.1548
   374.5  804.39   383.3805.1575   394.7  806.95   406.3  813.81   411.7  818.84
   421.7  833.56   440.1   850.9   472.1  864.94   484.6  874.23   494.5  879.51
   515.4  886.25   540.7  898.84   553.8  903.41   621.4  917.24   680.4  938.26
#Mann= 3 ,-1,0
       0      .1       0   367.1    .045       0   383.3      .1       0
Bank Sta=367.1,383.3
XS Rating Curve= 0 ,0
Exp/Cntr(USF)=0,0
Exp/Cntr=0.3,0.1

Type RM Length L Ch R = 1 ,7923    ,427.6,423.2,417.2
XS GIS Cut Line= 4
1628197.44755443541085.9952193061627973.66712078541247.995778637
1627845.98871385541252.1144369251627593.37767218541334.487602686
#Sta/Elev= 30
       0  923.06    43.5  909.11    62.7  900.87   116.7  889.21   128.4  883.47
   167.5  869.26   181.2   858.1   189.3  854.04   241.9  846.03   271.8  831.56
   284.6  828.45   294.4  820.81   307.5  805.39   316.6800.9061   327.2  800.11
   333.2800.8991   343.6  805.44   360.1     805   363.3  806.12   369.9  811.59
   392.9  823.13   416.8  827.11   468.2  854.79   488.9  869.55   506.2  879.51
   528.5  885.41   571.7  904.26   606.3  914.18   623.5  923.66   669.7  941.66
#Mann= 3 ,-1,0
       0      .1       0   316.6    .045       0   333.2      .1       0
Bank Sta=316.6,333.2
XS Rating Curve= 0 ,0
Exp/Cntr(USF)=0,0
Exp/Cntr=0.3,0.1

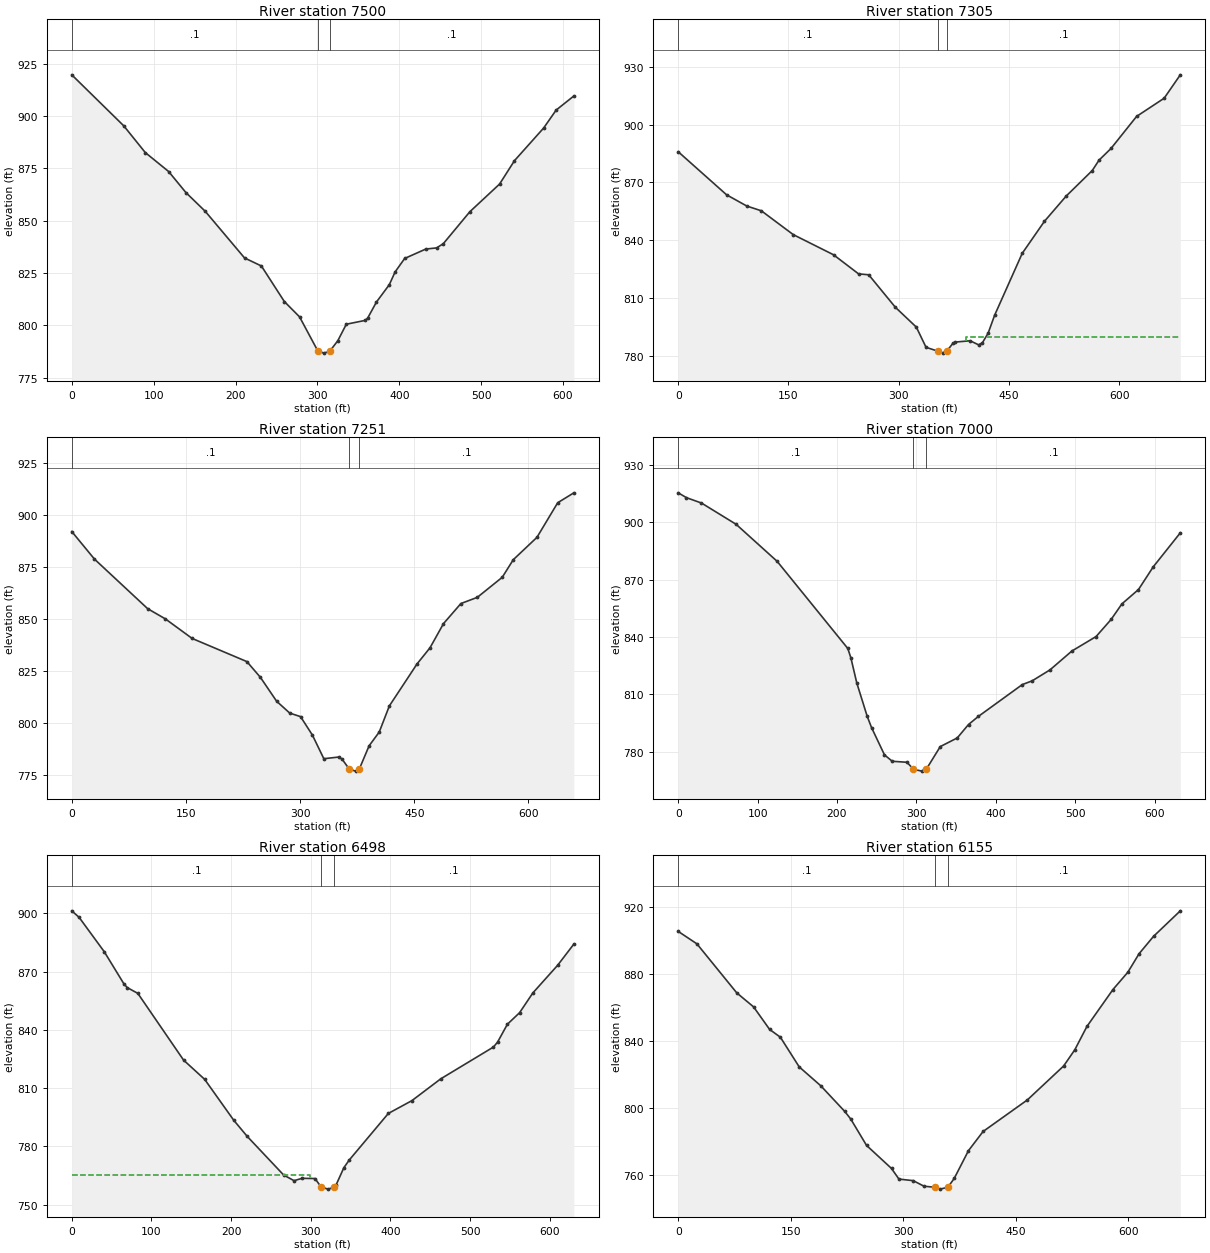
Type RM Length L Ch R = 1 ,7500    ,200,195.2,191.4
XS GIS Cut Line= 6
1627995.26946796540678.5452527251627922.12197646540737.184899226
1627717.91011456540902.1205929821627658.78490472540948.280605644
1627587.90282863540999.7778779721627507.29012898541048.849302143
#Sta/Elev= 30
       0  919.67    63.5   895.3    89.8  882.52   118.3  873.47   139.4  863.42
     163  854.46     211  832.17   231.6  828.33   259.6  811.35   278.2  804.02
   300.6787.6631     308  786.69   315.3787.6964   324.9   792.6   335.3   800.5
   358.6  802.35   361.5   803.5   372.1   811.1   387.8  819.38   394.9  825.49
   406.6  831.93   432.3  836.41   445.6  836.97   453.8     839   486.2  854.26
   522.5  867.48   540.7  878.66   576.3  894.24   591.6  902.83   613.2  909.56
#Mann= 3 ,-1,0
       0      .1       0   300.6    .045       0   315.3      .1       0
Bank Sta=300.6,315.3
XS Rating Curve= 0 ,0
Exp/Cntr(USF)=0,0
Exp/Cntr=0.3,0.1

Type RM Length L Ch R = 1 ,7305    ,49.2,53.9,57.7
XS GIS Cut Line= 4
1627861.32724139540461.8145896571627637.80765609540681.998061737
1627621.12709003540783.1934958741627442.08901425540981.136213198
#Sta/Elev= 30
       0   885.9    65.8  863.56    93.4  857.71   113.1  855.26   156.5   842.9
   211.3  832.44   245.4  822.52   259.2  822.05   295.4  805.21     324  794.89
   337.2  784.41     353 782.439   360.6  781.39   365.5782.4351   373.9  786.55
   377.2  787.13   397.2  787.81   408.6  785.71   413.8   786.7   421.7  791.76
   430.6  801.12   468.1  833.19   498.3   849.8   527.9   862.9   563.4  876.16
   572.6  881.54   588.9  887.61   623.7  904.24   661.2  913.68   683.2  925.83
#Mann= 3 ,-1,0
       0      .1       0     353    .045       0   365.5      .1       0
#XS Ineff= 2 , 0
                          391.06          789.96
Permanent Ineff=
       F       F
Bank Sta=353,365.5
XS Rating Curve= 0 ,0
Exp/Cntr(USF)=0,0
Exp/Cntr=0.3,0.1

Type RM Length L Ch R = 1 ,7251    ,255.1,250.8,248.8
XS GIS Cut Line= 3
1627824.62999604540424.0053065731627602.22244848540687.558250426
1627369.80656129540899.957458341
#Sta/Elev= 30
       0  892.23    29.8  878.97    99.7  855.13     123  850.21   158.2   840.8
   230.1  829.67   247.8  822.13   269.2   810.6   286.4  804.91   300.6  803.21
   316.2  794.32   331.2  782.97   350.7  783.77   355.1  782.82   364.7  777.92
   372.9     777   377.7777.9218   390.7  789.19     404   795.8   417.3  808.37
   453.7  828.57   470.7  836.31   488.4  847.93   511.3  857.59   532.9  860.58
   565.6  870.21   580.1  878.67   611.2  889.42   638.5  906.07   659.7  910.84
#Mann= 3 ,-1,0
       0      .1       0   364.7    .045       0   377.7      .1       0
Bank Sta=364.7,377.7
XS Rating Curve= 0 ,0
Exp/Cntr(USF)=0,0
Exp/Cntr=0.3,0.1

Type RM Length L Ch R = 1 ,7000    ,492.8,501.9,509.2
XS GIS Cut Line= 6
1627611.15737531540226.7902507331627527.91475964540388.198720559
1627444.99366564540542.5363383891627406.53737772540607.709764481
1627343.62674239540680.3392123881627272.76697597540756.404677063
#Sta/Elev= 30
       0   915.5    10.4  912.96    29.3  910.15    72.9  899.02   124.6  879.62
   213.6  833.99   217.5  829.07   224.9  815.96     238  798.51   243.5  792.57
   259.8  778.26   269.6   774.9   288.2  774.38   296.3770.7189   306.9  769.74
   312.5770.7268   330.1  782.59   351.5  787.12   365.7  794.16   378.1   798.4
   433.4  815.06   445.8  817.01   468.3  822.76   495.9  832.64   526.4  840.23
   545.4  849.22   558.9  857.32   579.8  864.85   598.4  876.74   632.5  894.55
#Mann= 3 ,-1,0
       0      .1       0   296.3    .045       0   312.5      .1       0
Bank Sta=296.3,312.5
XS Rating Curve= 0 ,0
Exp/Cntr(USF)=0,0
Exp/Cntr=0.3,0.1

Type RM Length L Ch R = 1 ,6498    ,350.6,342.8,334.9
XS GIS Cut Line= 6
 1627445.7541628540135.0565103141627349.78289805 540171.73228997
1627183.19300814540191.5144026431627008.34033947540199.893979058
1626921.28047422540210.9684319791626831.92927498540248.079906315
#Sta/Elev= 30
       0  901.23     9.2  897.88    40.8  880.17    65.4  863.68    69.6  861.74
    82.9  858.76   140.3  824.43   166.8  814.51   203.2  793.51   220.2  785.16
   265.9  765.29     279  762.37   288.9  763.59   305.3  763.48   313.1  759.02
   321.8  758.03   328.9759.0337   331.6  760.09   341.5  769.07   348.3  773.04
   397.3  796.98   426.9  803.57   463.1  814.79   529.2  831.14   534.4  833.69
   546.7  842.87     562  848.81   578.7     859   609.7  873.18   630.1  884.11
#Mann= 3 ,-1,0
       0      .1       0   313.1    .045       0   328.9      .1       0
#XS Ineff= 2 , 0
          298.83  765.49
Permanent Ineff=
       F       F
Bank Sta=313.1,328.9
XS Rating Curve= 0 ,0
Exp/Cntr(USF)=0,0
Exp/Cntr=0.3,0.1

Type RM Length L Ch R = 1 ,6155    ,146.7,154.8,163.6
XS GIS Cut Line= 4
1627256.50227179 539778.405619921626987.14201975539898.258576103
1626919.18415799540008.2267523941626702.95459787540124.372916117
#Sta/Elev= 30
       0  905.48    24.9  898.06    78.1  868.79   100.5  860.46   121.8  847.05
   136.2  842.37   161.3  824.69   190.1   813.4   221.9  798.19     230  793.61
   251.1  777.86   284.4   764.1   294.3  757.77   313.4  756.83   327.7  753.52
   341.8 752.902   349.1  751.78   359.6 752.906     368  758.16     387  774.71
   406.5  786.15   465.5  804.96   513.9  825.21   528.8  834.87     545  848.82
   579.7  870.83   599.6  881.16   614.5  892.16   633.8  902.53   669.5  917.75
#Mann= 3 ,-1,0
       0      .1       0   341.8    .045       0   359.6      .1       0
Bank Sta=341.8,359.6
XS Rating Curve= 0 ,0
Exp/Cntr(USF)=0,0
Exp/Cntr=0.3,0.1

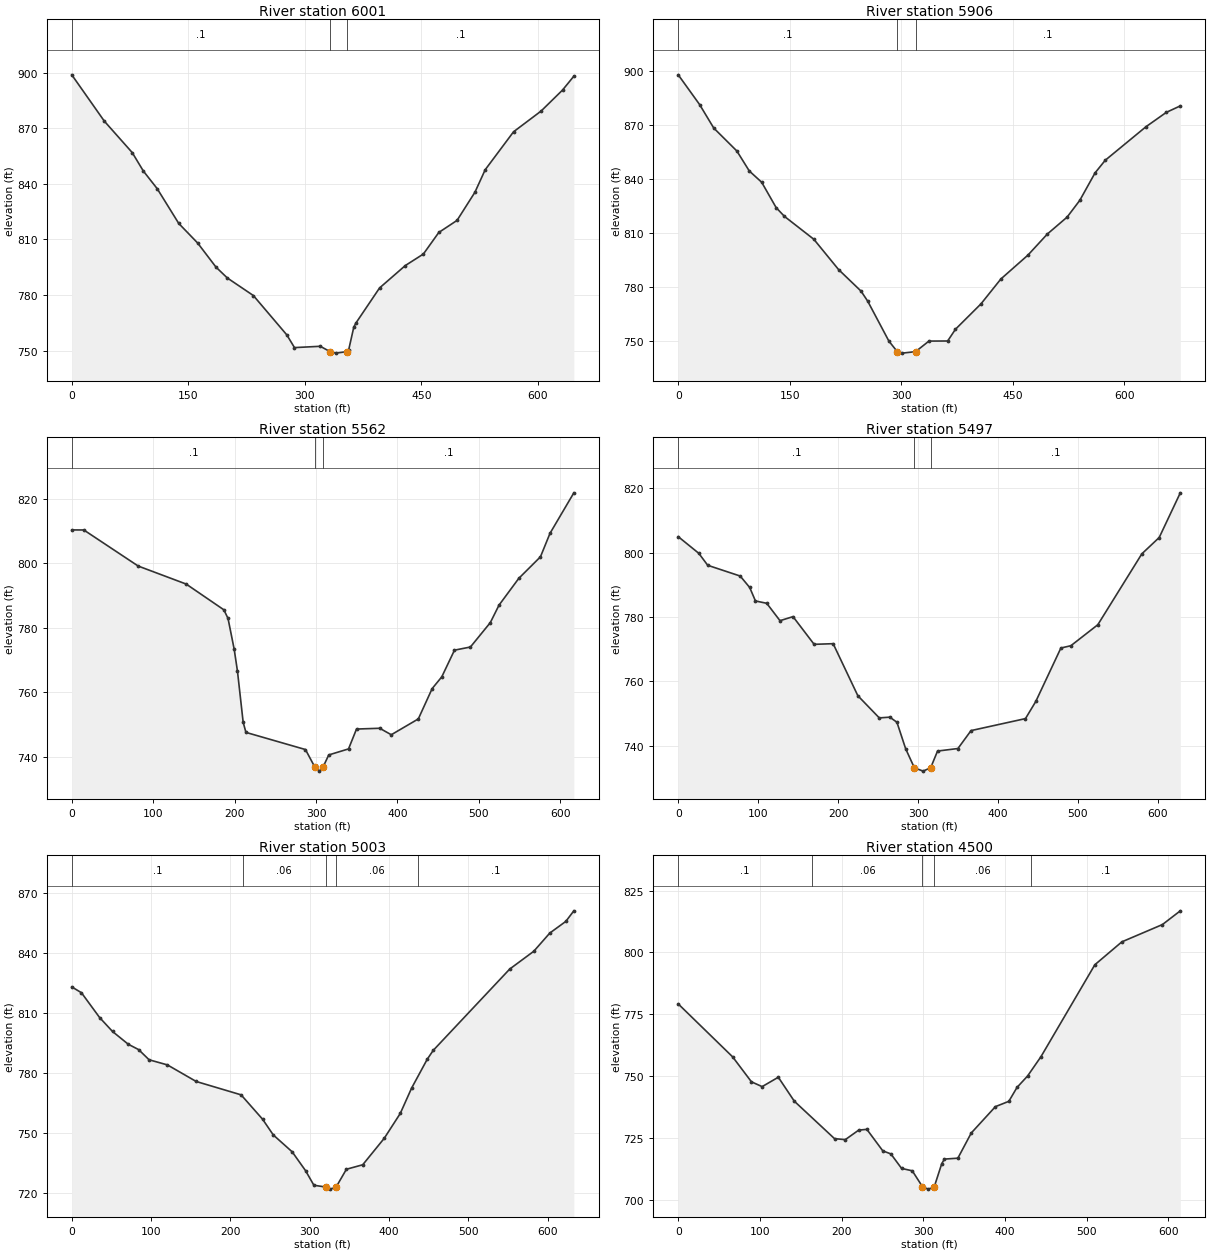
Type RM Length L Ch R = 1 ,6001    ,89,94.2,101.3
XS GIS Cut Line= 6
 1627203.2014983 539724.890992061627106.06422539539767.821024314
1627009.87773797539801.076535225 1626928.7197638539812.130646974
1626829.79542097539826.8031898141626576.24080998539863.771619812
#Sta/Elev= 30
       0  898.77    41.9  873.77    77.8  856.81    92.1  846.86   109.9  837.36
   137.7  818.56     162  808.01   185.6     795   200.2  789.14   233.7  779.66
   276.7  758.45   286.6  751.57   319.8  752.28   332.7749.3267   339.7  748.59
     354749.3709   356.3  750.26   362.9  762.57   365.7  764.86   396.1  783.77
   429.2  795.84   452.5  802.08   472.3   813.7   495.8  820.22   518.8   835.4
     532  847.54   568.5  868.03   603.9   879.2   631.5  890.53   646.1  898.03
#Mann= 3 ,-1,0
       0      .1       0   332.7    .045       0     354      .1       0
Bank Sta=332.7,354
XS Rating Curve= 0 ,0
Exp/Cntr(USF)=0,0
Exp/Cntr=0.3,0.1

Type RM Length L Ch R = 1 ,5906    ,355.9,344.1,333.1
XS GIS Cut Line= 4
1627199.66478741539693.1493933581626931.54013286539745.044487787
1626857.40428367539711.6833556541626549.74050956539804.353167135
#Sta/Elev= 30
       0  897.72    28.8  881.21    47.8   868.2    78.9  855.48    95.6  844.41
   112.3  838.15   131.8  824.05     143   819.2   182.5  806.52   215.8  789.72
     246  777.78     255  772.19   283.5  750.06   294.8744.2012   301.5  743.38
   319.4   744.2   337.4  750.06   362.6  750.11   373.1  756.62   407.4  770.68
   434.2  784.49   470.6  797.72   496.9  809.48   523.3  818.79   540.4  828.09
     561  843.36   574.7  850.35   629.5  868.94   656.9  876.91   675.7  880.49
#Mann= 3 ,-1,0
       0      .1       0   294.8    .045       0   319.4      .1       0
Bank Sta=294.8,319.4
XS Rating Curve= 0 ,0
Exp/Cntr(USF)=0,0
Exp/Cntr=0.3,0.1

Type RM Length L Ch R = 1 ,5562    ,70.8,64.7,59.3
XS GIS Cut Line= 4
 1626959.4862446539268.8213147451626754.11511519539433.658668615
1626681.15431921539462.4826867781626531.62972499539693.074832083
#Sta/Elev= 30
       0  810.34    14.8  810.32    81.6  799.13   140.5  793.55   186.8  785.56
   191.9  782.89   199.4  773.43   203.5  766.53   210.5  750.67   213.9  747.55
     287  742.23   298.4736.8417   304.2  735.54   308.6736.8108   315.6  740.56
   339.9  742.43   349.7  748.59   378.2  748.83   392.4  746.82   425.6  751.73
   442.6  761.14   454.4  764.77     470  773.05   489.6  774.03     514  781.59
   524.7  787.01     549  795.32   575.6     802   587.3  809.27   616.6  821.84
#Mann= 3 ,-1,0
       0      .1       0   298.4    .045       0   308.6      .1       0
Bank Sta=298.4,308.6
XS Rating Curve= 0 ,0
Exp/Cntr(USF)=0,0
Exp/Cntr=0.3,0.1

Type RM Length L Ch R = 1 ,5497    ,498.2,494.5,492.3
XS GIS Cut Line= 6
1626834.19797122539141.7792973971626734.18734448539294.036210731
1626695.50435098539358.6755171421626652.35876797539449.484718725
 1626554.7323228539584.4988843951626515.43154839539680.202433139
#Sta/Elev= 30
       0  804.97    25.7   799.8    36.9  796.07    77.5  792.73    89.4  789.17
    96.6  784.98   110.7  784.26   127.3  778.85   143.6  780.11     170   771.5
   193.8   771.7   224.7  755.52   251.5  748.63   264.7  748.86   273.6  747.27
   284.5  739.04   295.4  733.12   306.3  732.08   315.8733.1339   324.4  738.32
   349.9  739.11   366.3  744.68   434.4  748.41   447.3  753.74   478.7  770.35
   491.2  771.07   524.9  777.59     580  799.64   601.7  804.71   628.1   818.6
#Mann= 3 ,-1,0
       0      .1       0   295.4    .045       0   315.8      .1       0
Bank Sta=295.4,315.8
XS Rating Curve= 0 ,0
Exp/Cntr(USF)=0,0
Exp/Cntr=0.3,0.1

Type RM Length L Ch R = 1 ,5003    ,504.1,502.9,499.9
XS GIS Cut Line= 6
1626256.55640997539095.2977630651626255.89663438 539196.66829522
1626245.39501497539290.3656143991626225.50168206539366.650238723
1626196.44530971 539464.958112971626138.28466488539714.393965811
#Sta/Elev= 30
       0  822.94    12.2  820.03    35.1  807.64    51.4  800.67    71.2  794.31
    84.3  791.62    97.5  786.54   120.6  783.98   156.9   775.7   213.5  769.03
   240.6  756.86   254.1     749   277.9  740.58   294.8  731.16   305.3  723.88
     320723.0018   325.8  721.94   333.4723.0265   346.3  731.86   366.9  734.11
     394  747.32   414.2  759.72   428.5  772.38   448.2  786.79   455.8  791.24
   552.3  831.87   582.6  840.74   602.8  849.83     623  855.66   633.1  860.93
#Mann= 5 ,-1,0
       0      .1       0  215.66     .06       0     320    .045       0
   333.4     .06       0     437      .1       0
Bank Sta=320,333.4
XS Rating Curve= 0 ,0
Exp/Cntr(USF)=0,0
Exp/Cntr=0.3,0.1

Type RM Length L Ch R = 1 ,4500    ,70.5,71.8,73.1
XS GIS Cut Line= 6
1625728.61225589539063.9142956441625723.84093997 539157.79009214
1625731.33206671539420.1829400661625730.82681839539495.228065565
1625722.53648064539583.0005278141625709.78420955539677.037741303
#Sta/Elev= 30
       0  779.19    66.6  757.79    89.6  747.71   102.7  745.76   122.5  749.56
   142.1  739.87   191.3  724.74   204.5  724.33   220.9  728.18   230.9  728.49
   250.4   719.8   260.3  718.56   273.4  712.71   286.5  711.73     299705.2955
   306.2  704.33   313.4705.2731   322.6  714.65   325.9  716.47   342.3  716.84
   358.7  727.02   388.3  737.68   404.7  739.82   414.7  745.44   427.6  750.04
   444.1  757.91     510  795.03   543.1  804.29   592.7  811.27   614.6  816.82
#Mann= 5 ,-1,0
       0      .1       0     164     .06       0     299    .045       0
   313.4     .06       0  431.54      .1       0
Bank Sta=299,313.4
XS Rating Curve= 0 ,0
Exp/Cntr(USF)=0,0
Exp/Cntr=0.3,0.1

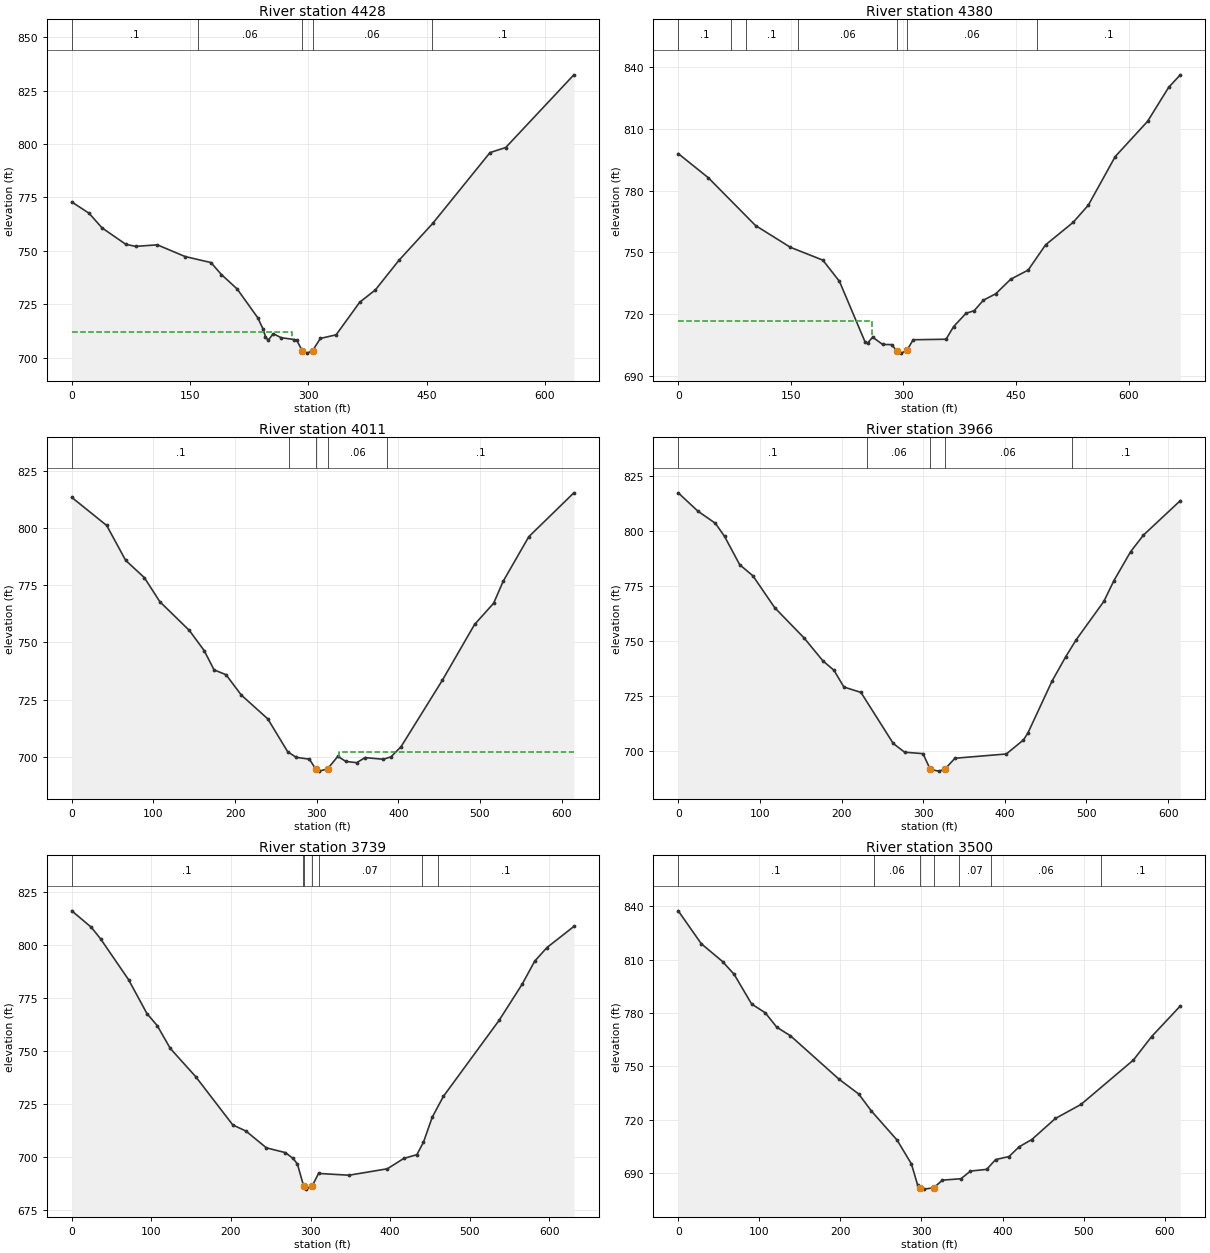
Type RM Length L Ch R = 1 ,4428    ,44.6,48.2,52.4
XS GIS Cut Line= 4
1625643.43653465539072.4786961661625663.20609443539340.603350718
1625648.37892459539427.0951747671625681.74005673539705.104609211
#Sta/Elev= 30
       0  772.85    21.9  767.58    38.4  760.72    68.6  753.01    81.1  752.07
   108.5  752.78   143.6  747.32   176.5  744.48   189.7  738.89   209.6  732.18
   235.8  718.66   242.3  713.57   245.6  709.83   248.9  708.07   255.5  711.18
   265.4  709.33     282  708.46   285.3  708.03   292.2  703.28   298.6  702.09
   305.4703.2909   315.2  708.97   335.2  710.67   365.1  725.93   384.9  731.67
   414.7  745.48   457.6  762.79   530.3  795.97   550.2  798.34   636.6  832.37
#Mann= 5 ,-1,0
       0      .1       0     160     .06       0   292.2    .045       0
   305.4     .06       0  456.61      .1       0
#XS Ineff= 2 , 0
          279.87  712.02
Permanent Ineff=
       F       F
Bank Sta=292.2,305.4
XS Rating Curve= 0 ,0
Exp/Cntr(USF)=0,0
Exp/Cntr=0.3,0.1

Type RM Length L Ch R = 1 ,4380    ,376.5,368.5,355.3
XS GIS Cut Line= 4
1625598.95502514539071.243098679 1625638.4941447539328.247375854
1625591.54144022539377.6712753111625639.72974219539714.989389103
#Sta/Elev= 30
       0  797.99      40  786.29     103  763.07   149.5  752.51   192.7  746.28
   214.8  735.99   249.1  706.45   252.4  706.09     259  708.94   272.3  705.38
   284.3   705.3   290.8702.4411     297  701.17   304.6702.4869     313  707.66
   356.8  707.91   366.8  714.01   383.3  720.46   394.3  721.78   406.5  726.83
   423.1     730     443  737.05   466.2  741.47   489.4  753.71     526  764.58
   546.3  772.94   582.2  796.55   625.3  813.64   653.5   830.2   668.9   836.2
#Mann= 7 ,-1,0
       0      .1       0      70     .06       0      90      .1       0
     160     .06       0   290.8    .045       0   304.6     .06       0
   478.2      .1       0
#XS Ineff= 2 , 0
          258.79  716.52
Permanent Ineff=
       F       F
Bank Sta=290.8,304.6
XS Rating Curve= 0 ,0
Exp/Cntr(USF)=0,0
Exp/Cntr=0.3,0.1

Type RM Length L Ch R = 1 ,4011    ,45.3,45.3,45.2
XS GIS Cut Line= 6
1625095.55969399539308.4791130171625280.73681707539485.604743023
1625353.00143632539554.7263239371625403.37469515539610.929623608
1625458.99958389539679.7136067641625516.84231598539754.832551022
#Sta/Elev= 30
       0   813.3    42.8  801.02      66  785.81    88.9  778.27   107.9  767.76
   144.1  755.19   162.2  746.41   174.3     738     189  735.89   207.6  727.04
   240.1  716.62   264.5  702.26   274.9  699.84   291.1  699.03   298.7 694.794
     303  693.81   313.3694.7791   325.9  700.26   335.7  698.05   349.1  697.49
   359.2  699.72   381.7  698.99     391  700.04   403.3  704.46   453.8   733.4
   493.4  757.83   516.8  767.12   528.4  776.66   559.8  796.12     615  815.28
#Mann= 5 ,-1,0
       0      .1       0  266.25     .06       0   298.7    .045       0
   313.3     .06       0  386.25      .1       0
#XS Ineff= 2 , 0
                          327.82          702.17
Permanent Ineff=
       F       F
Bank Sta=298.7,313.3
XS Rating Curve= 0 ,0
Exp/Cntr(USF)=0,0
Exp/Cntr=0.3,0.1

Type RM Length L Ch R = 1 ,3966    ,226.1,226.9,225.9
XS GIS Cut Line= 6
1625055.22134375539332.4811386291625240.39846683539509.606768635
1625312.66308608539578.7283495491625363.03634491 539634.93164922
1625418.66123365539703.7156323761625476.50396574539778.834576634
#Sta/Elev= 30
       0  817.49    24.2  809.11    45.5  803.61    56.7  797.66    75.3  784.75
    91.5  779.67   118.2  765.15   154.2  751.36   177.2  740.95   190.8  736.63
   202.9  729.02   223.8  726.57   263.4  703.29   277.3  699.33   299.8  698.66
   308.7691.5046   318.9   690.7   326.3691.5091     339  696.57   401.9  698.52
   422.9  704.93   428.1  707.91     458  731.81   474.5  742.72   487.5  750.57
   521.3  768.02   533.7   777.5   554.1  790.67   569.9  798.25     615  813.93
#Mann= 5 ,-1,0
       0      .1       0  231.25     .06       0   308.7    .045       0
   326.3     .06       0  481.72      .1       0
Bank Sta=308.7,326.3
XS Rating Curve= 0 ,0
Exp/Cntr(USF)=0,0
Exp/Cntr=0.3,0.1

Type RM Length L Ch R = 1 ,3739    ,239.8,239.4,238.2
XS GIS Cut Line= 2
1624878.19970951539516.0010817281625379.30313455539899.036302517
#Sta/Elev= 30
       0  815.94    24.5  808.22    36.2  802.75    71.3  783.57    94.4   767.6
   107.3  761.94   123.8  751.15   155.6  737.93   202.3  715.14   218.7  712.32
   244.5  704.38   268.4  702.13   278.1  699.37   283.5  696.72   291.2 686.489
   294.3  684.95   302.2 686.575     310  692.33   348.3   691.5   396.4  694.52
     417  699.38   433.5  701.17   441.8  707.04   452.8  718.79   466.8   728.6
   536.8  764.39   565.7  781.36   581.5  792.23   596.8  798.61   630.7  808.58
#Mann= 7 ,-1,0
       0      .1       0     290     .06       0   291.2    .045       0
   302.2     .06       0     310     .07       0     440     .06       0
     460      .1       0
Bank Sta=291.2,302.2
XS Rating Curve= 0 ,0
Exp/Cntr(USF)=0,0
Exp/Cntr=0.3,0.1

Type RM Length L Ch R = 1 ,3500    ,215.3,209.6,203.6
XS GIS Cut Line= 6
1624716.90233706539734.856523305 1624796.9504053539783.665808886
1625022.40894389539918.1087814721625083.93736413539961.345899731
1625162.21443856540005.0738306491625253.39371814540041.259781897
#Sta/Elev= 30
       0   837.5    28.4  818.99    54.7  808.94      69  801.72    90.5  785.05
   107.3   780.1   121.6  771.95   138.4  767.16   198.2  742.74   222.6  734.36
   237.9  724.97     270  708.36   287.6  694.99   295.2  683.17   297.6681.5764
   302.8  680.81   315.1681.5833   325.8  685.87   348.7  686.67   360.4  690.98
   380.4  691.94   391.4  697.45   407.9  699.15   420.5  704.66   436.1  708.75
   465.2  720.62   496.6  728.46   561.4  753.52   583.8   766.7   619.2  783.94
#Mann= 7 ,-1,0
       0      .1       0  241.26     .06       0   297.6    .045       0
   315.1     .06       0  346.26     .07       0  386.26     .06       0
  521.12      .1       0
Bank Sta=297.6,315.1
XS Rating Curve= 0 ,0
Exp/Cntr(USF)=0,0
Exp/Cntr=0.3,0.1

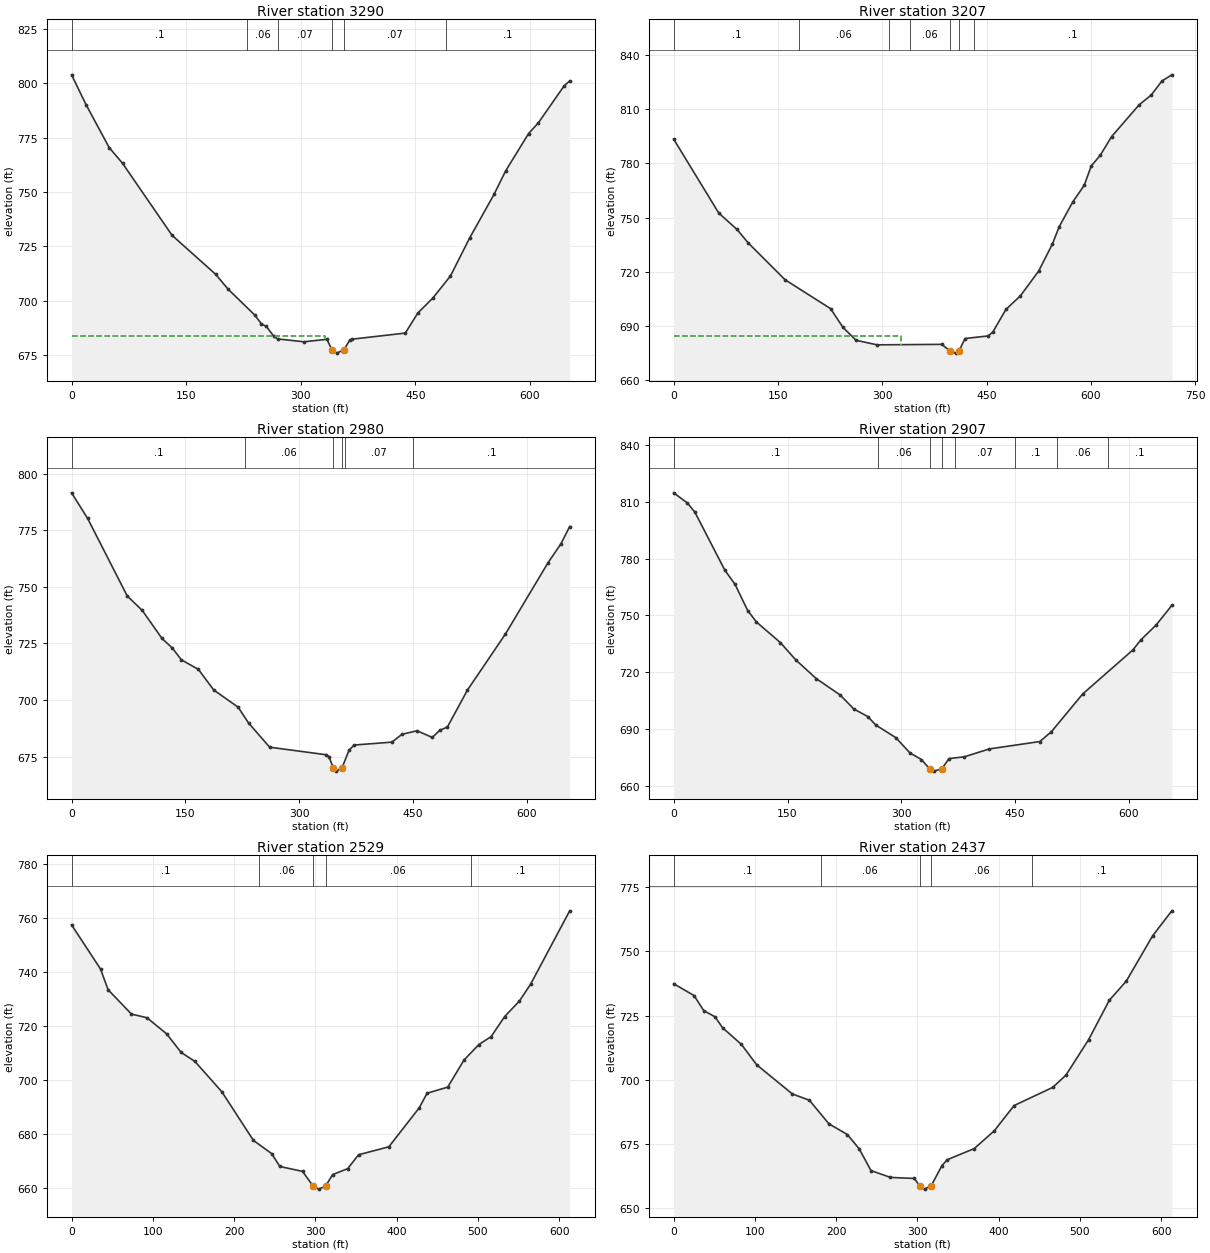
Type RM Length L Ch R = 1 ,3290    ,82.8,82.8,82.7
XS GIS Cut Line= 4
1624660.35014379539915.3599181991624878.30954039540103.294295883
1625009.52999345540082.1655788651625240.83384291540091.061880767
#Sta/Elev= 30
       0  803.99      19  790.23    49.3  770.48    66.7  763.28   131.6  730.11
   188.7  712.16     205   705.3   239.9  693.41   248.6  689.33     255  688.18
     265  683.56     270  682.42   304.2  681.11   334.2  682.24   340.8  677.53
   347.4  675.89   356.8677.5355   364.1  681.82   367.4  682.32     437  685.12
   453.4  694.37   473.1  701.28   496.1  711.41   521.4  729.02   553.1  748.94
   568.3  759.74   598.4  776.98     611  781.81   644.7   798.8   652.2   801.2
#Mann= 6 ,-1,0
       0      .1       0     230     .06       0     270     .07       0
   340.8    .045       0   356.8     .07       0  490.71      .1       0
#XS Ineff= 2 , 0
          331.74  683.65
Permanent Ineff=
       F       F
Bank Sta=340.8,356.8
XS Rating Curve= 0 ,0
Exp/Cntr(USF)=0,0
Exp/Cntr=0.3,0.1

Type RM Length L Ch R = 1 ,3207    ,215.3,227.4,235.3
XS GIS Cut Line= 4
1624640.33346451539949.2770692011624903.88640836540182.804994134
1625035.10686142540161.6762771161625266.41071088540170.572579018
#Sta/Elev= 30
       0  793.28    64.8  752.47    91.1  743.39   107.3  735.92   160.1  715.65
   225.7  699.64   243.2  689.44   262.4  682.16   292.6  679.66   385.9  679.92
   397.4 676.186   405.8  675.08   410.3676.1935   419.1  683.16   452.3  684.58
     459  686.69   477.8   699.2   498.7  706.72     525  720.43   544.7  735.32
   554.5  744.93   574.2   758.7   590.6  767.85   600.5  778.38   613.6  784.42
     630  794.75   669.4  812.21   686.9  817.68   702.3  825.41   716.5  828.82
#Mann= 7 ,-1,0
       0      .1       0     180     .06       0     310     .07       0
     340     .06       0   397.4    .045       0   410.3     .06       0
  432.13      .1       0
#XS Ineff= 2 , 0
          326.35  684.72
Permanent Ineff=
       F       F
Bank Sta=397.4,410.3
XS Rating Curve= 0 ,0
Exp/Cntr(USF)=0,0
Exp/Cntr=0.3,0.1

Type RM Length L Ch R = 1 ,2980    ,73.3,73.2,72.1
XS GIS Cut Line= 6
1624609.41477685539973.0841365361624685.00583302540057.456671199
 1624745.9079422540143.8292018681624772.44758727540220.538694119
1624787.97380294540319.3258981161624827.68238494540572.480575537
#Sta/Elev= 30
       0   791.5    21.1  780.23    73.3  745.95    93.2  739.53   119.1   727.2
   132.8  722.93   144.6  717.76   167.2  713.49   187.3   704.4   219.4  696.84
   233.2  689.84     261  679.14   335.8  675.78   339.1     675   344.8670.1234
   349.1  668.56   356.5 670.125   365.7  677.82   372.3  680.08   422.1  681.37
   435.4  684.83   455.3  686.39   475.3  683.43   485.2  686.59   495.2  688.03
   521.7  704.39   571.6  729.07     628  760.71   644.6  768.84   656.4  776.61
#Mann= 6 ,-1,0
       0      .1       0  228.97     .06       0   344.8    .045       0
   356.5     .06       0  360.14     .07       0  450.14      .1       0
Bank Sta=344.8,356.5
XS Rating Curve= 0 ,0
Exp/Cntr(USF)=0,0
Exp/Cntr=0.3,0.1

Type RM Length L Ch R = 1 ,2907    ,382,378.1,371.3
XS GIS Cut Line= 6
1624538.11900639539972.5022527761624613.71006256540056.874787439
1624674.61217174540143.2473181081624701.15181681540219.956810359
1624716.67803248540318.7440143561624756.38661448540571.898691777
#Sta/Elev= 30
       0  814.75    17.9  809.43    27.9  804.55    67.5  773.82    80.8  766.46
    97.5  752.58   109.1  746.52   140.7  735.61   160.9  726.49     188  716.58
   219.4  707.97   237.3   700.6   255.9  696.55   266.2  692.13   292.9  685.38
   311.2   677.4   326.4  673.88   337.3668.9709     343  667.75   353.2668.9654
   362.9  674.38   382.9  675.31   416.1  679.49   482.5  683.38   497.8   688.6
   538.9  708.49   605.4  731.87   615.3  736.97   635.6  744.86   656.4  755.29
#Mann= 8 ,-1,0
       0      .1       0  268.97     .06       0   337.3    .045       0
   353.2     .06       0  370.14     .07       0  450.14      .1       0
  505.14     .06       0  572.64      .1       0
Bank Sta=337.3,353.2
XS Rating Curve= 0 ,0
Exp/Cntr(USF)=0,0
Exp/Cntr=0.3,0.1

Type RM Length L Ch R = 1 ,2529    ,92,92,92
XS GIS Cut Line= 6
1624186.14554579540270.5501627561624254.07979312540335.177658164
1624447.36713621540512.7904919171624500.10882863540566.241500505
1624560.84197488540629.4710328361624625.79460088540697.346225165
#Sta/Elev= 30
       0  757.34    35.6  741.01      45  733.31    73.7  724.32    92.8  722.96
     117     717   134.8  710.13   151.8  706.79   184.9  695.57   223.8  677.55
   246.2  672.68   256.3   667.9   284.2  666.09   297.3660.6271   304.1  659.52
   312.5 660.635   321.3   664.9   339.8   667.1   353.2  672.25   390.4  675.18
   427.8   689.6   437.5  695.02   462.9  697.28     483  707.33   501.2  713.04
   516.3  715.97     533  723.42   551.1  729.14     565  735.44     613  762.54
#Mann= 5 ,-1,0
       0      .1       0  231.26     .06       0   297.3    .045       0
   312.5     .06       0  491.36      .1       0
Bank Sta=297.3,312.5
XS Rating Curve= 0 ,0
Exp/Cntr(USF)=0,0
Exp/Cntr=0.3,0.1

Type RM Length L Ch R = 1 ,2437    ,103,106.5,111
XS GIS Cut Line= 6
1624118.52891128540333.1050830561624186.46315861540397.732578464
 1624379.7505017540575.3454122171624432.49219412540628.796420805
1624493.22534037540692.0259531361624558.17796637540759.901145465
#Sta/Elev= 30
       0   737.4    25.1  732.78      37  726.92    50.9  724.51    60.2  720.24
    83.4  713.75   102.1  705.84   146.1  694.46     167  692.03     191  682.85
   213.7  678.69   228.2  673.14   242.8  664.65   266.7  661.98   296.1  661.58
   302.5658.7556   308.7  657.42   316.9  658.74     330  666.51   336.5  668.85
   369.9  673.22   394.5  680.12   418.9  689.96   466.5  697.04   482.7   701.8
   510.6  715.62   536.1  730.94     557  738.43   589.4  756.05     613  765.78
#Mann= 5 ,-1,0
       0      .1       0  181.26     .06       0   302.5    .045       0
   316.9     .06       0  441.36      .1       0
Bank Sta=302.5,316.9
XS Rating Curve= 0 ,0
Exp/Cntr(USF)=0,0
Exp/Cntr=0.3,0.1