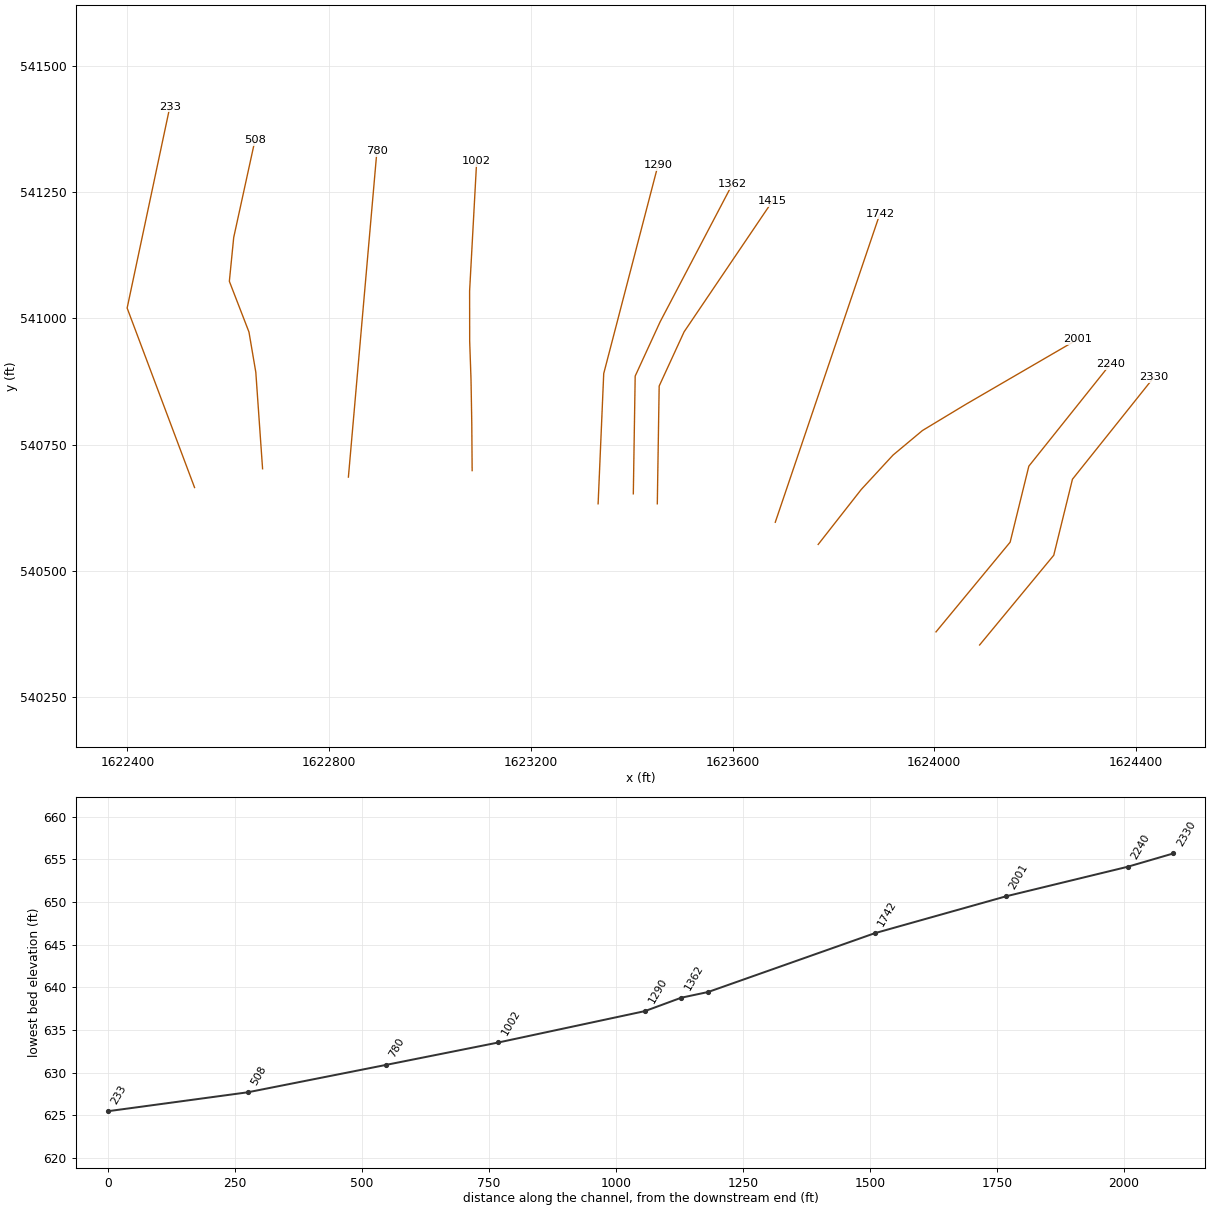
HEC-RAS study JimRn.prj: JimRn

--- JimRn.g01 (geometry) --- (continued)

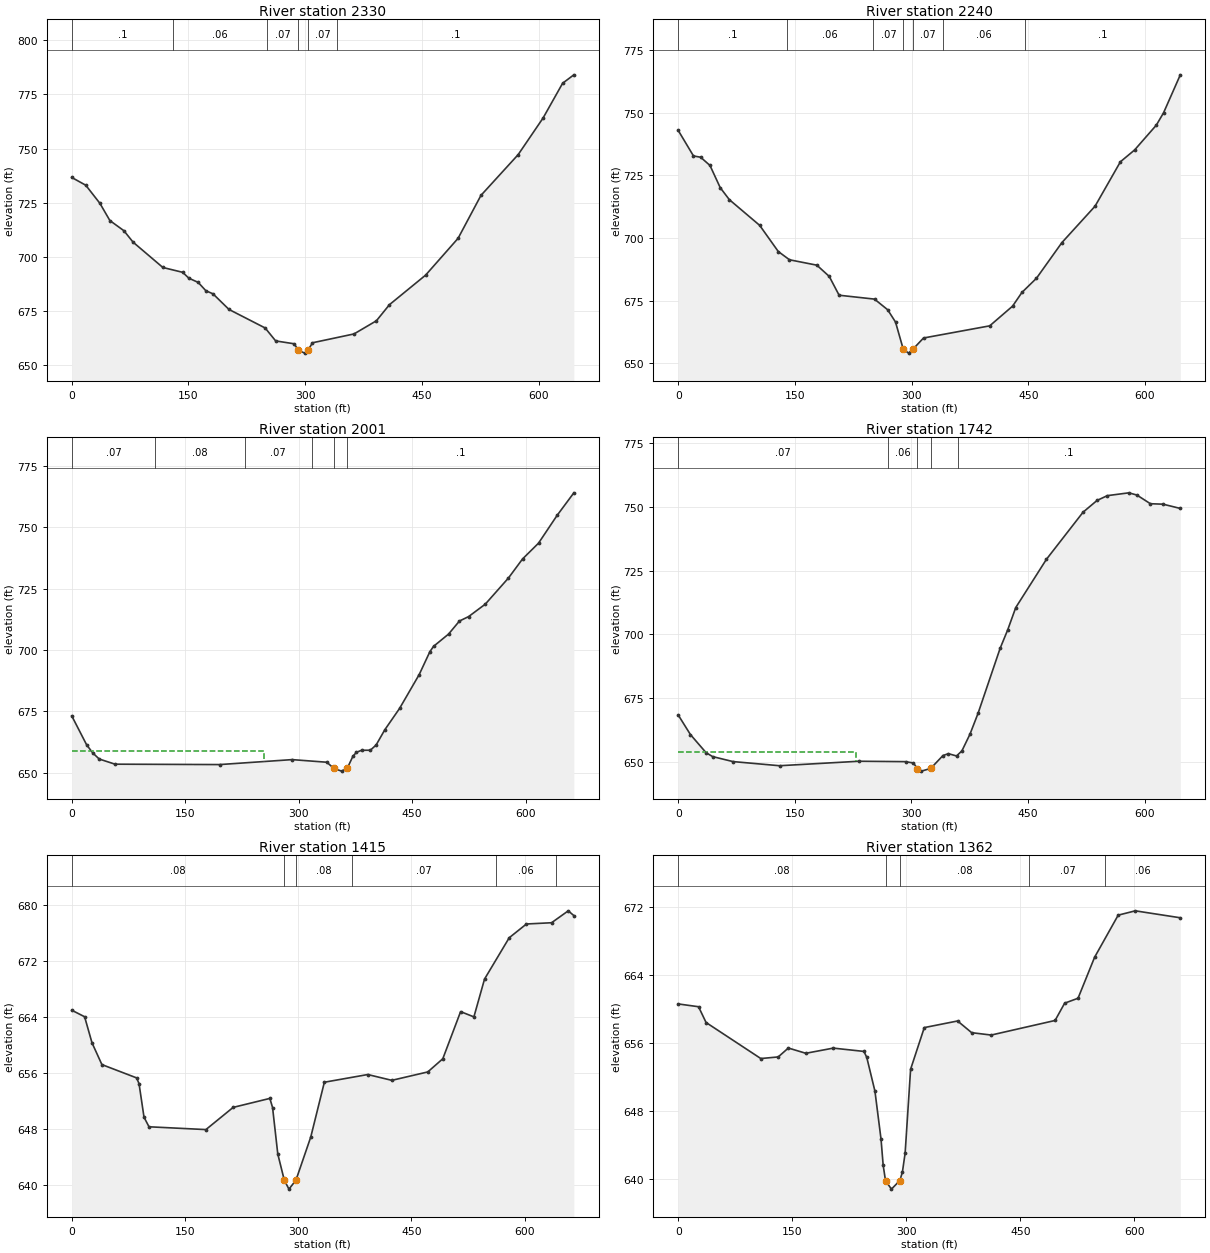
Type RM Length L Ch R = 1 ,2330    ,90.3,90.3,90.3
XS GIS Cut Line= 4
1624089.99834406540352.5143088931624237.03444494540530.440346938
1624274.10236954 540681.183240281624435.96564026540883.821228053
#Sta/Elev= 30
       0  736.65      18  733.08    36.2  724.72      49  716.79      67  712.12
    78.8  706.85   117.1  695.17   142.6  692.94   150.5  690.23   162.5   688.3
   172.4  684.45   181.5  683.04   202.1  675.83   248.6  667.29   262.1  661.33
   285.8  660.01   291.2657.1363   299.3   655.7   303.9657.1338   309.4  660.47
   362.8  664.54   391.6  670.61   408.4  678.04   454.8  691.63   496.6  708.62
     526   728.4   573.8  747.17   605.8  764.03     631  780.09   645.4  783.96
#Mann= 6 ,-1,0
       0      .1       0     130     .06       0  250.82     .07       0
   291.2    .045       0   303.9     .07       0  340.82      .1       0
Bank Sta=291.2,303.9
XS Rating Curve= 0 ,0
Exp/Cntr(USF)=0,0
Exp/Cntr=0.3,0.1

Type RM Length L Ch R = 1 ,2240    ,244.3,239.1,234.2
XS GIS Cut Line= 4
1624003.50652001540378.4618561081624150.54262089540556.387894152
1624187.61054549540707.1307874951624349.47381621540909.768775268
#Sta/Elev= 30
       0  742.93    19.6  732.76    28.8  732.25    40.8  728.97      54   720.1
    65.7  715.33   104.7  705.08   128.6  694.65     143  691.36   178.2   689.2
   194.1  684.73   206.8  677.22   252.3  675.67   269.2  671.43   279.3  666.53
   289.3655.6428   296.2  654.13   301.4655.6014   315.3  660.16   400.4  665.01
   429.8  672.87   441.8  678.33   460.5  683.99   493.2  698.21   535.8  712.72
   568.4  730.44   586.6  735.13   614.6  745.06   623.9  749.99   645.4  765.11
#Mann= 7 ,-1,0
       0      .1       0     140     .06       0  250.82     .07       0
   289.3    .045       0   301.4     .07       0  340.82     .06       0
  446.05      .1       0
Bank Sta=289.3,301.4
XS Rating Curve= 0 ,0
Exp/Cntr(USF)=0,0
Exp/Cntr=0.3,0.1

Type RM Length L Ch R = 1 ,2001    ,250.7,258.6,263.1
XS GIS Cut Line= 6
1623769.86046913 540551.909520681623855.25346981540660.887479648
1623918.29927547540729.1314376441623976.71976231540777.865920231
1624062.33671705540829.5620110631624283.86645772540958.358997554
#Sta/Elev= 30
       0  673.16    19.7  661.35      28     658    36.3   655.6    57.2   653.5
   195.4  653.34   291.3  655.36   337.2  654.29346.4156651.7786   356.7  650.67
364.1155651.7985   371.7  656.76   376.3  658.32     383  659.16   394.7  659.19
   402.3   661.3   413.8  667.51   433.3   676.2   459.3  690.02   473.4  699.33
   478.3  701.51   498.1   706.5   512.5  711.82   524.5   713.6   546.6  718.67
   577.3  729.35   595.9   737.1     617  743.52   641.5  754.81   663.7  764.03
#Mann= 6 ,-1,0
       0     .07       0     110     .08       0  228.45     .07       0
  317.44      .1       0346.4156    .045       0364.1155      .1       0
#XS Ineff= 2 , 0
          253.97  658.93
Permanent Ineff=
       F       F
Bank Sta=346.4156,364.1155
XS Rating Curve= 0 ,0
Exp/Cntr(USF)=0,0
Exp/Cntr=0.3,0.1

Type RM Length L Ch R = 1 ,1742    ,327.8,327.6,326.7
XS GIS Cut Line= 2
1623684.75287709540595.8812508481623892.21122049541207.578278074
#Sta/Elev= 30
       0  668.37    15.7  660.69    35.8  653.59    44.2  652.05    70.4  650.09
   130.3  648.46   232.4  650.22   292.5  650.06   302.5  649.52   307.7647.3667
   312.9  646.34   324.8647.4037   340.6  652.47   347.6  653.19     358   652.3
   364.9  654.27   375.3  660.84   385.7  669.03   414.1  694.56   423.8  701.77
   434.2  710.57   473.6  729.49   520.8  748.02   538.8  752.63     552  754.51
   579.7  755.62   590.1  754.74   607.4  751.34   623.7  751.16   645.9  749.49
#Mann= 5 ,-1,0
       0     .07       0     270     .06       0   307.7    .045       0
   324.8     .06       0     360      .1       0
#XS Ineff= 2 , 0
          228.07  653.91
Permanent Ineff=
       F       F
Bank Sta=307.7,324.8
XS Rating Curve= 0 ,0
Exp/Cntr(USF)=0,0
Exp/Cntr=0.3,0.1

Type RM Length L Ch R = 1 ,1415    ,53,53,52.7
XS GIS Cut Line= 4
1623450.79783204540632.491546742 1623454.5046245540866.019471675
1623503.92852396540973.5164529931623679.38336703541232.991925141
#Sta/Elev= 30
       0  664.99      17  664.06    26.8  660.34    39.9  657.23    85.9  655.33
    89.1  654.51    95.7  649.72   102.3  648.35   177.7  647.95   213.8  651.12
   262.4   652.4     266   651.1   272.9  644.47   281.5640.7367   287.7  639.45
     297640.7361   316.6  646.89   334.6  654.71   392.1  655.81     424  654.98
   471.6  656.18   491.5  658.06   515.1  664.79   532.7  664.04   546.8  669.44
   579.5  675.34   602.3   677.3   635.6  677.48   657.7  679.18   665.1   678.5
#Mann= 6 ,-1,0
       0     .08       0   281.5    .045       0     297     .08       0
  371.87     .07       0  561.87     .06       0  641.87      .1       0
Bank Sta=281.5,297
XS Rating Curve= 0 ,0
Exp/Cntr(USF)=0,0
Exp/Cntr=0.3,0.1

Type RM Length L Ch R = 1 ,1362    ,69.2,71.4,72.6
XS GIS Cut Line= 4
1623403.22732882540652.2611065241623406.93412127540885.789031457
1623456.35802073540993.2860127761623599.68732916541266.353057274
#Sta/Elev= 30
       0  660.62    26.7  660.29    36.6  658.43   108.6  654.18   131.5  654.37
   144.8  655.42   167.8   654.8   203.9  655.41   244.2  655.02   247.9  654.33
   258.7  650.33   266.7  644.68   269.5  641.61   272.6639.7733   280.4  638.78
   291.4  639.79   294.8  640.78   298.4  643.03   305.6  652.92   323.6  657.83
   367.4  658.61   385.9  657.23   411.6  656.95   495.6  658.67   508.2  660.71
   525.8  661.29   547.6  666.13   578.6  671.09   601.1   671.6   660.3  670.78
#Mann= 5 ,-1,0
       0     .08       0   272.6    .045       0   291.4     .08       0
  461.87     .07       0  561.87     .06       0
Bank Sta=272.6,291.4
XS Rating Curve= 0 ,0
Exp/Cntr(USF)=0,0
Exp/Cntr=0.3,0.1

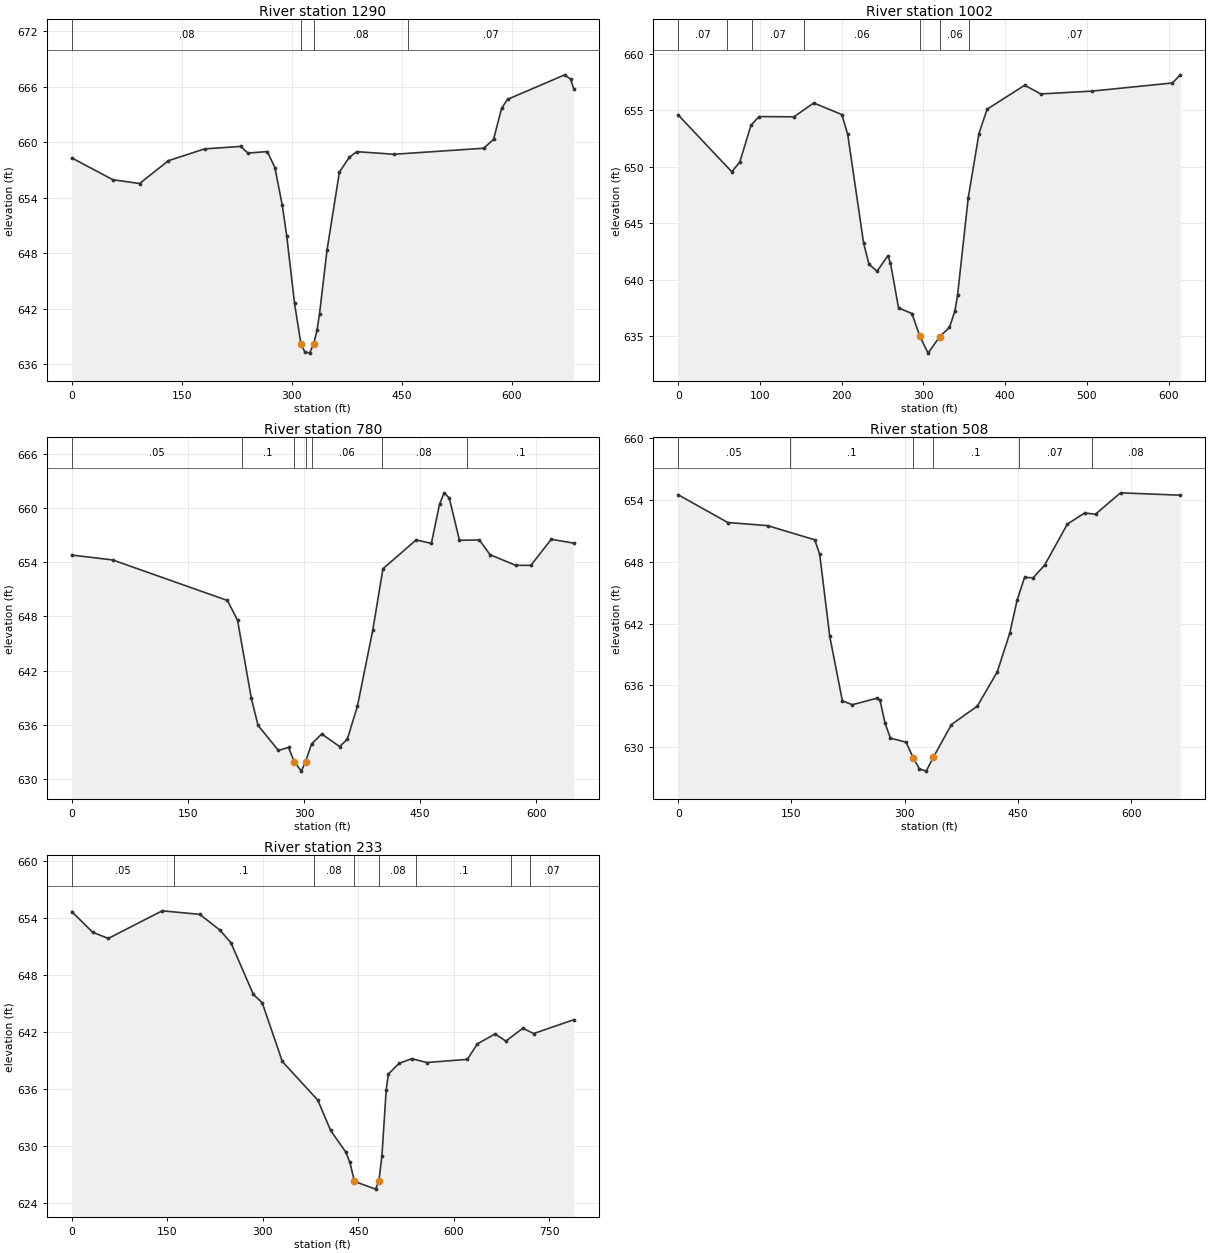
Type RM Length L Ch R = 1 ,1290    ,285.8,288.5,291.5
XS GIS Cut Line= 3
1623333.41607083540632.4915467421623344.53644821540890.731421403
1623452.03342953541303.420981867
#Sta/Elev= 30
       0   658.3      56  655.94    92.5  655.53   131.9     658   181.2  659.27
   230.4  659.54   240.3  658.82   266.8  658.98   277.1  657.24   287.1  653.21
   293.2   649.9   303.9  642.59   312.6638.2052   317.7  637.38   324.4  637.21
     330638.2124   334.6  639.69     338  641.48   348.2  648.33   365.1  656.77
   378.7  658.38   388.8  658.97   439.7  658.69   561.8  659.34   575.3  660.29
   586.4  663.66   594.4  664.62   672.4  667.27   680.4  666.81   684.9  665.72
#Mann= 4 ,-1,0
       0     .08       0   312.6    .045       0     330     .08       0
  458.48     .07       0
Bank Sta=312.6,330
XS Rating Curve= 0 ,0
Exp/Cntr(USF)=0,0
Exp/Cntr=0.3,0.1

Type RM Length L Ch R = 1 ,1002    ,221.1,221.2,221.4
XS GIS Cut Line= 6
1623083.60278213540698.2673261461623082.87870222540792.011233151
1623081.34458455540879.4969505671623078.71401238 540954.45086889
1623078.56112556541054.5070992261623092.57094005541311.982962221
#Sta/Elev= 30
       0  654.58    65.5  649.56    75.3  650.42      89  653.67    98.8  654.44
   141.5  654.42   165.8  655.64   200.1  654.62   207.3  652.88   226.8  643.24
   233.4  641.38   243.2  640.77   256.3  642.12   259.6  641.52   269.5  637.53
   285.9  637.03   295.7     635   305.6  633.53     320634.9952   331.8   635.8
   338.4  637.25   341.7  638.65   354.8  647.28   367.9  652.94   377.8  655.09
   423.8  657.21   443.5  656.44   505.9  656.69   604.5  657.41   614.2  658.13
#Mann= 7 ,-1,0
       0     .07       0      60     .08       0      90     .07       0
  153.75     .06       0   295.7    .045       0     320     .06       0
  356.25     .07       0
Bank Sta=295.7,320
XS Rating Curve= 0 ,0
Exp/Cntr(USF)=0,0
Exp/Cntr=0.3,0.1

Type RM Length L Ch R = 1 ,780     ,263.5,272,275.9
XS GIS Cut Line= 2
1622838.19119716540685.4576429861622894.68856736541331.410909015
#Sta/Elev= 30
       0  654.79    52.8  654.25     201  649.77   214.1  647.58   231.8     639
   240.5  635.97   266.8  633.19     280  633.52   287.3631.9391   296.5   630.9
     302631.9588   309.6  633.89   322.8  635.01   345.9  633.62   355.8  634.42
   368.9  638.08   388.7  646.48   401.9  653.28   444.7  656.46   464.4  656.08
   474.9  660.39   480.9  661.67   487.5   661.1   500.7  656.42   526.4  656.46
   540.2  654.83   573.1  653.66   592.9  653.65   619.2  656.53   648.4  656.11
#Mann= 7 ,-1,0
       0     .05       0     220      .1       0   287.3    .045       0
     302      .1       0     310     .06       0     400     .08       0
     510      .1       0
Bank Sta=287.3,302
XS Rating Curve= 0 ,0
Exp/Cntr(USF)=0,0
Exp/Cntr=0.3,0.1

Type RM Length L Ch R = 1 ,508     ,270.7,275.4,266.3
XS GIS Cut Line= 6
1622667.98779972540701.9743397241622654.57083181540893.441804558
1622640.98785372540973.2162513141622602.09652731541073.750827149
1622610.75923964541160.7349051391622652.78441806541353.058667481
#Sta/Elev= 30
       0  654.49    65.7   651.8   118.3   651.5   180.9  650.12   187.4   648.7
   200.7  640.76   217.4   634.5   230.7  634.13   263.9  634.78   267.3  634.54
   273.9  632.35     281  630.89   301.8   630.5   311.1 629.005   319.3  627.92
   328.4  627.69   337.8  629.02   361.9  632.21   396.1  633.99   422.5  637.31
     439  641.04   448.8  644.25   458.7  646.48     470  646.44   485.3  647.67
   515.4  651.65   538.2  652.72   552.7  652.61   585.8  654.68     665  654.45
#Mann= 6 ,-1,0
       0     .05       0  148.44      .1       0   311.1    .045       0
   337.8      .1       0  450.69     .07       0   548.1     .08       0
Bank Sta=311.1,337.8
XS Rating Curve= 0 ,0
Exp/Cntr(USF)=0,0
Exp/Cntr=0.3,0.1

Type RM Length L Ch R = 1 ,233     ,,,
XS GIS Cut Line= 3
1622533.10539804540664.7419405771622399.39495522541020.675372878
1622484.14101053541419.923455672
#Sta/Elev= 30
       0  654.71    32.7  652.54    57.3  651.88     142  654.79   200.9  654.42
   232.5  652.77     250  651.42   285.1  645.99   299.1   645.1   330.6  638.92
   386.4  634.84   406.5  631.65     430   629.4   436.7  628.29   443.9626.2833
     477  625.47   482.2626.2947     487  628.93   493.7  635.89   497.1  637.59
   513.9  638.72     534  639.21   557.5  638.81   621.2  639.14     637  640.78
   664.8  641.82   681.6  641.07   708.4  642.42   725.2  641.86   788.4  643.32
#Mann= 8 ,-1,0
       0     .05       0     160      .1       0     380     .08       0
   443.9    .045       0   482.2     .08       0  540.22      .1       0
  690.22     .06       0  720.22     .07       0
Bank Sta=443.9,482.2
XS Rating Curve= 0 ,0
Exp/Cntr(USF)=0,0
Exp/Cntr=0.3,0.1
LCMann Table=0

Chan Stop Cuts=-1
Use User Specified Reach Order=0
Composite Channel Slope=5